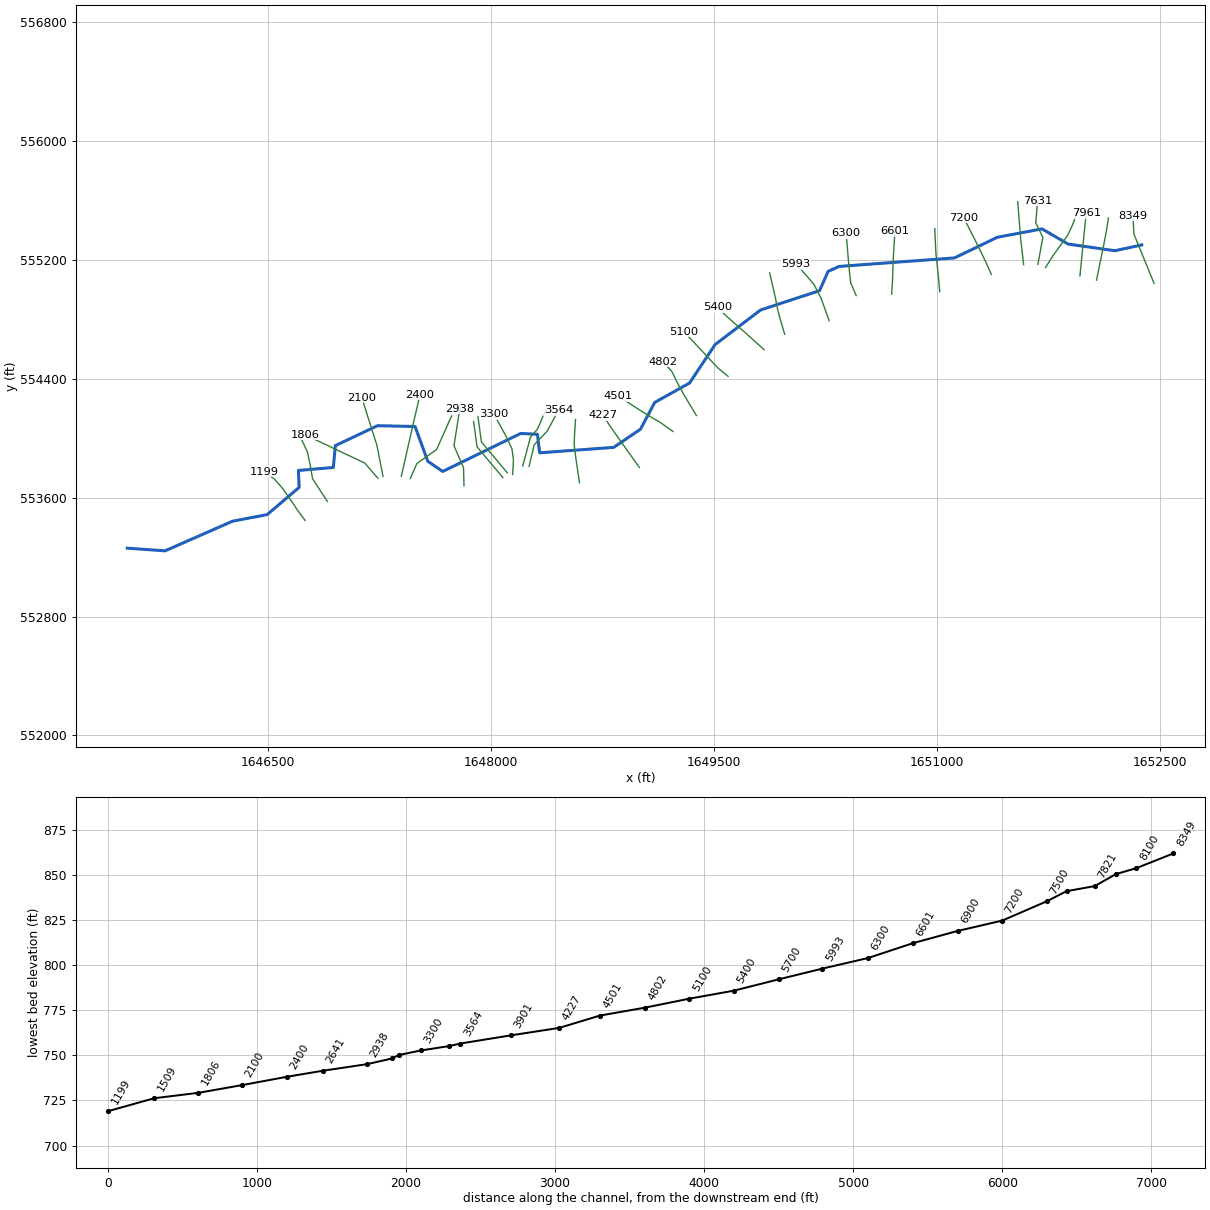
--- BrittRn.prj (project) ---

Proj Title=BrittRn
Current Plan=p01
Default Exp/Contr=0,0
English Units
Geom File=g01
Flow File=f01
Plan File=p01
BEGIN DESCRIPTION:
---------- MODELED AS PART OF WVEM CTP PROGRAM, 2025----------
Stream Name: Britt Run
Flood Zone: AFH
Marshall County, WV
HEC-RAS Version: RAS 6.6
Vertical Datum: NAVD88
Projection: NAD 1983 StatePlane West Virginia N FIPS 4701 (US Feet)
Terrain: 1-meter West Virginia FEMA R3 South Central (collected 2018-2019)
Land Use: 2024 NLCD
Hydrologic Method:
Duda et al., "Estimation of magnitude and frequency of floods for rural, unregulated streams in and near Virginia and West Virginia." September 8, 2025.
Additional Model Notes:
None
END DESCRIPTION:
DSS File=dss
DSS Export Rating Curves= 0
DSS Export Rating Curve Sorted= 0
DSS Export Volume Flow Curves= 0
DXF OffsetX= 0
DXF OffsetY= 0
DXF ScaleX= 0
DXF ScaleY= 0

--- BrittRn.p01 (plan) ---

Plan Title=Floodplain
Program Version=6.60
Short Identifier=Floodplain
Geom File=g01
Flow File=f01
Subcritical Flow
K Sum by GR= 0
Std Step Tol= 0.01
Critical Tol= 0.01
Num of Std Step Trials= 20
Max Error Tol= 0.3
Flow Tol Ratio= 0.001
Split Flow NTrial= 30
Split Flow Tol= 0.02
Split Flow Ratio= 0.02
Log Output Level= 0
Friction Slope Method= 1
Unsteady Friction Slope Method= 2
Unsteady Bridges Friction Slope Method= 1
Parabolic Critical Depth
Global Vel Dist= 0 , 0 , 0
Global Log Level= 0
CheckData=False
Encroach Param=-1 ,0,0, 0
Flow Ratio Tolerance=0.1
Flow Ratio Min Ratio=0.5
Flow Ratio Max Ratio=4
Flow Ratio Max Iterations= 10
Computation Interval=0.1SEC
Output Interval=1SEC
Instantaneous Interval=Max Profile
Mapping Interval=1HOUR
Computation Time Step Use Courant=        0
Computation Time Step Use Time Series=    0
Computation Time Step Count To Double=0
Computation Time Step Max Doubling=0
Computation Time Step Max Halving=0
Computation Time Step Residence Courant=0
Run HTab= 0
Run UNet= 0
Run Sediment= 0
Run PostProcess= 0
Run WQNet= 0
Run RASMapper= 0
UNET Theta= 0
UNET Theta Warmup= 0
UNET ZTol= 0
UNET ZSATol= 0
UNET MxIter= 0
UNET Max Iter WO Improvement= 0
UNET MaxInSteps= 0
UNET DtIC= 0
UNET DtMin= 0
UNET MaxCRTS= 0
UNET WFStab= 0
UNET SFStab= 0
UNET WFX= 1
UNET SFX= 1
UNET Gravity=32.17405
UNET 1D Methodology=Finite Difference
UNET DSS MLevel= 1
UNET Pardiso=0
UNET DZMax Abort= 0
UNET Use Existing IB Tables= 0
UNET Froude Reduction=False
UNET Froude Limit= 0
UNET Froude Power= 0
UNET D1 Cores= 0
UNET WindReference=Eulerian
UNET WindDragFormulation=Hsu (1988)
UNET D2 Coriolis=0
UNET D2 Cores= 0
UNET D2 Theta= 1
UNET D2 Theta Warmup= 1
UNET D2 Z Tol= 0.01
UNET D2 Volume Tol= 0.01
UNET D2 Max Iterations= 20
UNET D2 Advanced Convergence=0
UNET D2 WS Max Tol=0.15
UNET D2 WS RMS Tol=0.002
UNET D2 WS Stall Tol=1
UNET D2 Equation= 0
UNET D2 RampUpFraction=0.1
UNET D2 TimeSlices= 1
UNET D2 Turbulence Formulation=Non-Conservative (original)
UNET D2 Eddy Viscosity=0.3
UNET D2 Transverse Eddy Viscosity=0.1
UNET D2 Smagorinsky Mixing=0
UNET D2 BCVolumeCheck=0
UNET D2 Cores=0
UNET D2 SolverType=PARDISO (Direct)
UNET D2 Minimum Iterations= 3
UNET D2 Maximum Iterations= 30
UNET D2 Restart Number= 10
UNET D2 Relaxation Coeff=1.3
UNET D2 SOR Precondition Iterations= 10
UNET D2 ILUT Maximum Fill= 8
UNET D2 ILUT Tolerance=1E-08
UNET D2 Convergence Tolerance=0.00001
PS Theta= 1
PS WS Tol= 0.01
PS Volume Tol= 0.01
PS Max Iterations= 20
PS Equation= 0
PS Advance Time Step=-1
PS Target Courant=0.9
PS Time Slices= 1
PS Iterate With 2D=0
PS Project Initial WSE from DS=-1
PS Ramp Up Initial WSE from US=-1
PS Cores=0
UNET D1D2 MaxIter= 0
UNET D1D2 ZTol=0.01
UNET D1D2 QTol=0.1
UNET D1D2 MinQTol=1
DSS File=dss
Write IC File= 0
Write IC File at Fixed DateTime=0
Write IC File at Sim End=0
Echo Input=False
Echo Parameters=False
Echo Output=False
Write Detailed= 0
HDF Write Warmup=0
HDF Write Time Slices=0
HDF Flush=0
HDF Compression= 1
HDF Chunk Size= 1
HDF Spatial Parts= 1
HDF Use Max Rows=0
HDF Fixed Rows= 1
Calibration Method= 0
Calibration Iterations= 20
Calibration Max Change=0.05
Calibration Tolerance=0.2
Calibration Maximum=1.5
Calibration Minimum=0.5
Calibration Optimization Method= 1
WQ AD Non Conservative
WQ ULTIMATE=-1
WQ Max Comp Step=1HOUR
WQ Output Interval=15MIN
WQ Output Selected Increments= 0
WQ Create Restart=0
WQ Fixed Restart=0
WQ System Summary=0
WQ Write To DSS=0
Sorting and Armoring Iterations= 10
XS Update Threshold= 0.02
Bed Roughness Predictor= 0
Processes Affected by Predictor=Sediment Only
Hydraulics Update Threshold= 0.02
Energy Slope Method= 1
Volume Change Method= 1
Sediment Retention Method= 0
Sediment TS Multiplier= 1
Warm Up Method= 0
XS Weighting Method= 0
Number of US Weighted Cross Sections= 1
Number of DS Weighted Cross Sections= 1
Upstream XS Weight=0
Main XS Weight=1
Downstream XS Weight=0
Number of DS XS's Weighted with US Boundary= 1
Upstream Boundary Weight= 1
Weight of XSs Associated with US Boundary= 0
Number of US XS's Weighted with DS Boundary= 1
Downstream Boundary Weight= 0.5
Weight of XSs Associated with DS Boundary= 0.5
Percentile Method= 0
Sediment Output Level= 3
Mass or Volume Output= 0
Output Increment Type= 1
Profile and TS Output Increment= 1
Transport Output Increment 1
XS Output Flag= 0
XS Output Increment= 10
Read HDF5 Sediment Hotstart= 0
Sediment Hotstart Type= 0
Write Gradation File= 0
Read Gradation Hotstart= 0
Write HDF5 File= 1
Write Binary Output= 1
Write DSS Sediment File= 0
DSS Sediment Output Type= 1
SV Curve= 0
Specific Gage Flag= 0
Subcell Erosion Methods= 0
Subcell Deposition Methods= 0
Advection Scheme= 1
Matrix Solver= 0
Implicit Weighting Factor= 1
Maximum Outer Loop Convergence Iterations= 5
Convergence Maximum Absolute= 0.001
Convergence RMSE= 0.0001
Grain Fractions Max Abs Error= 0.001
Max Subgrid Regions= 1
Max Subgrid Length Scale= 3.402823E+38
Initial Layer Thickness= 3
Min Layer Thickness= 0.1
Max Layer Thickness= 6
Number of Layers= 5

--- BrittRn.f01 (steady flow) ---

Flow Title=Flow
Program Version=6.60
Number of Profiles= 1
Profile Names=P100yr
River Rch & RM=BrittRn,Main            ,8349
     948
River Rch & RM=BrittRn,Main            ,5400
    1060
Boundary for River Rch & Prof#=BrittRn,Main            , 1
Up Type= 0
Dn Type= 3
Dn Slope=0.018308
DSS Import GetInterval= 0
DSS Import GetPeak= 0
DSS Import FillOption= 0

--- BrittRn.g01 (geometry) ---

Geom Title=Geometry
Program Version=6.60

River Reach=BrittRn         ,Main
Reach XY= 30
     1652378.562      555299.683     1652198.153      555260.753
      1651883.23      555305.381     1651707.253      555407.612
     1651407.024      555351.335     1651118.588      555212.303
     1650342.184      555155.045     1650268.435      555121.766
      1650210.99      554992.251      1649813.74       554861.71
     1649508.522      554629.639     1649336.028      554370.493
     1649102.314      554240.357     1649006.164      554059.941
     1648826.108      553937.862     1648328.071      553901.491
     1648312.946       554026.09     1648200.231       554031.42
     1647675.934      553775.955     1647575.412      553844.953
     1647490.088      554078.307     1647237.649      554083.708
     1646954.067      553949.832     1646940.045      553802.653
     1646705.157       553782.74      1646710.22      553668.672
     1646495.145      553485.687     1646262.829      553441.436
     1645808.534      553242.071     1645554.037      553259.973

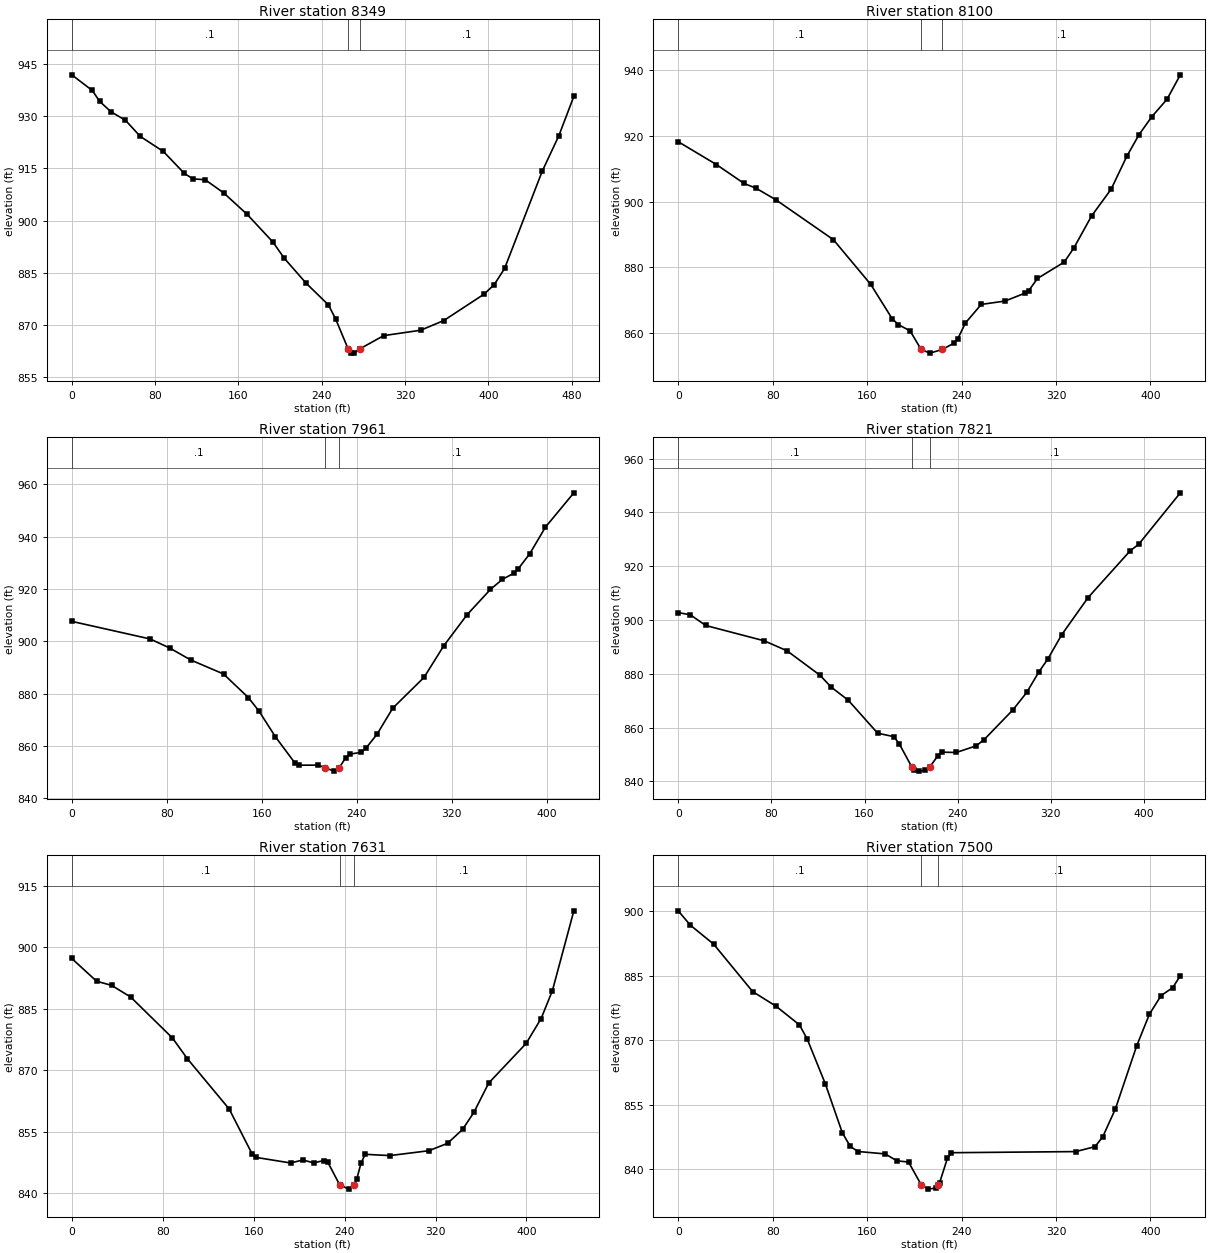
Type RM Length L Ch R = 1 ,8349    ,252,248.8,243.4
XS GIS Cut Line= 3
1652461.13001339555040.4667306561652325.55355795555372.831152428
1652318.36216369555495.849056545
#Sta/Elev= 30
       0  941.91    19.7  937.41    26.8  934.28    37.6  931.31    51.6  928.84
    65.8  924.21      88  919.88   108.1  913.58   116.3  912.03   128.2  911.75
   145.9  907.98   168.5  901.79   193.3  893.82     204  889.23   225.2  881.99
   246.5   875.8   253.6  871.63  265.41863.1597   267.7   862.1   271.3  861.94
  276.63863.1579   299.6  866.97   335.1  868.52   357.3   871.3   395.9  878.87
   405.8  881.64   415.7  886.28   451.8  914.19   467.8  924.41   482.2  935.73
#Mann= 3 ,-1,0
       0      .1       0  265.41    .045       0  276.63      .1       0
Bank Sta=265.41,276.63
XS Rating Curve= 0 ,0
Exp/Cntr=0.3,0.1

Type RM Length L Ch R = 1 ,8100    ,137.9,139,138.6
XS GIS Cut Line= 6
1652074.05989301555063.081444249  1652091.555921555148.814212427
1652106.55293825555222.2996297631652126.54764892555320.280076832
1652140.42294925555393.9958086761652153.99608484555480.740057752
#Sta/Elev= 30
       0  918.26    32.4  911.28    55.8  905.52    65.9  904.08    82.6  900.57
   131.4  888.39     163  874.77   181.2  864.29   186.4  862.49   196.4  860.56
  205.76854.8955   213.2  853.78  223.61854.8942   233.3  856.76   236.6  858.01
   243.3  862.99   256.7  868.64   276.8  869.66   293.5  872.04   296.8  872.78
   304.3  876.55     327  881.55   335.2   885.9   350.1   895.6   366.7  903.78
     380  913.83   390.4  920.44   401.1  925.86   414.1  931.24   425.3  938.66
#Mann= 3 ,-1,0
       0      .1       0  205.76    .045       0  223.61      .1       0
Bank Sta=205.76,223.61
XS Rating Curve= 0 ,0
Exp/Cntr(USF)=0,0
Exp/Cntr=0.3,0.1

Type RM Length L Ch R = 1 ,7961    ,144.5,140.3,136.4
XS GIS Cut Line= 2
1651962.47598576555091.5704703721652004.07887572555512.309131117
#Sta/Elev= 30
       0  907.64    65.9  900.93    82.4  897.47   100.2  892.88   127.8  887.53
   148.8  878.47   157.8  873.25   171.4  863.59   187.9  853.53   191.2  852.68
   207.6   852.7  213.35851.6825   220.8  850.41  225.22851.6796   230.7  855.57
     234  856.88   243.9   857.6   247.8  859.22   257.1  864.54   270.3  874.47
   296.7  886.26   313.1   898.2   332.9  910.19   352.6  919.87   362.6  923.69
   372.5  926.08   375.8  927.63   385.6  933.43   398.9  943.66   422.8  956.76
#Mann= 3 ,-1,0
       0      .1       0  213.35    .045       0  225.22      .1       0
Bank Sta=213.35,225.22
XS Rating Curve= 0 ,0
Exp/Cntr(USF)=0,0
Exp/Cntr=0.3,0.1

Type RM Length L Ch R = 1 ,7821    ,179.7,189.4,193.7
XS GIS Cut Line= 6
1651730.50947682555147.0421933761651777.23871406555221.209039786
1651820.92038523555282.1672512081651879.13713231555363.567022794
 1651911.9464499555432.7463463781651943.96180581555518.942696282
#Sta/Elev= 30
       0  902.77    10.4  901.95    23.6  897.98      74  892.26    93.5  888.55
   121.8  879.46   131.2  875.12   146.1  870.15   171.2  857.94   185.3  856.62
     190  853.82   200.6845.3715   202.5  844.37   206.5  843.82     212  844.06
   215.9  845.29   222.9  849.49   226.7  850.88   238.8  850.75   255.9  853.23
   262.7  855.53   287.6  866.68   299.3  873.09   309.7  880.69   317.5  885.57
   329.4  894.58     352  908.36   388.3  925.82   395.4  928.14   431.2  947.31
#Mann= 3 ,-1,0
       0      .1       0   200.6    .045       0   215.9      .1       0
Bank Sta=200.6,215.9
XS Rating Curve= 0 ,0
Exp/Cntr(USF)=0,0
Exp/Cntr=0.3,0.1

Type RM Length L Ch R = 1 ,7631    ,134.1,131.2,129.3
XS GIS Cut Line= 4
1651679.55889046555168.5488994711651712.76270641555350.110190945
1651665.42960707555448.3087104591651677.43949795555595.959721814
#Sta/Elev= 30
       0  897.25    21.8  891.71    35.1  890.68    51.8  887.85    88.5  877.88
   101.8  872.77   138.5  860.53   158.5  849.66   161.8  848.75   192.5  847.38
   203.4  848.11   212.8   847.4   221.7  847.97   225.3  847.54  235.58842.0984
   243.5     841  248.45842.0983   250.8  843.52   254.4  847.29   258.1  849.49
   279.9  849.18   314.2  850.37   330.6  852.17   343.8  855.55   353.7  859.69
   366.8  866.87   399.7  876.52   412.9   882.6   422.8  889.37   441.7  908.87
#Mann= 3 ,-1,0
       0      .1       0  235.58    .045       0  248.45      .1       0
Bank Sta=235.58,248.45
XS Rating Curve= 0 ,0
Exp/Cntr(USF)=0,0
Exp/Cntr=0.3,0.1

Type RM Length L Ch R = 1 ,7500    ,297,300.5,302.5
XS GIS Cut Line= 6
1651583.53856434555166.6343867631651574.07237592555253.854684755
 1651564.8387986 555328.356832341651556.91033676555428.042328507
 1651550.9644825555502.8062865881651544.02781659555590.030849665
#Sta/Elev= 30
       0  900.09    10.2  896.77      30  892.35      63  881.34    82.8  877.94
   102.7  873.59   109.3  870.28   124.6   859.9     139  848.53   145.7  845.37
   152.3  844.18   175.3  843.62   185.2  842.02   195.1  841.73  205.92 836.394
   211.6  835.44   218.1  835.68     220836.3939   221.4  836.92     228   842.6
   231.3   843.9   336.7  844.16   353.1  845.31   359.7  847.65   370.2     854
   388.4  868.76   399.1  876.05     409   880.4   418.9  882.24   425.3  885.02
#Mann= 3 ,-1,0
       0      .1       0  205.92    .045       0     220      .1       0
Bank Sta=205.92,220
XS Rating Curve= 0 ,0
Exp/Cntr(USF)=0,0
Exp/Cntr=0.3,0.1

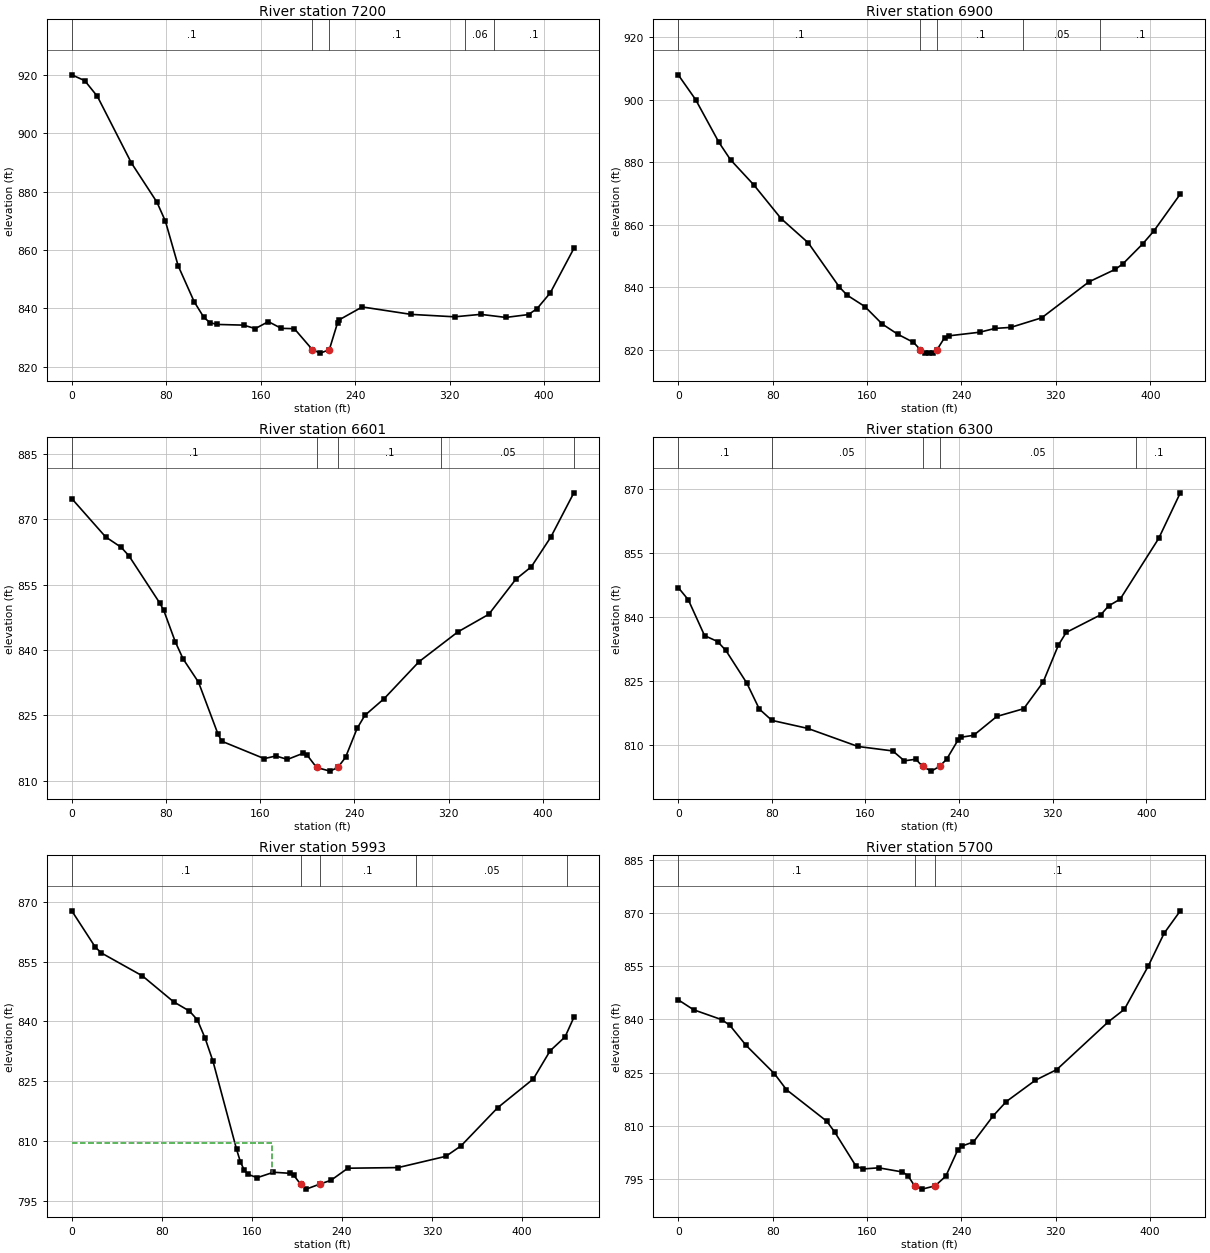
Type RM Length L Ch R = 1 ,7200    ,302,299.5,297.2
XS GIS Cut Line= 6
1651366.71878801555101.2208036781651330.73493609555181.136654332
1651298.45809776555248.8615844991651254.05989259555338.470001087
1651220.12032792555405.3514290011651180.52427851555483.379816249
#Sta/Elev= 30
       0  920.01      11  918.01    21.7  912.62    50.5  889.82    72.1  876.41
    79.3  869.87    90.1   854.6   103.7  842.26   111.9   836.9     117  835.15
   122.8  834.51   145.6  834.27   155.4  833.08   166.5  835.47   177.4  833.17
   188.5  833.05  203.82 825.842   210.4  824.68   218.1825.8386   225.1  835.09
   226.4  836.07     246   840.5   287.4  837.95   324.2  837.12   346.3  837.96
   367.6  836.91   386.8  837.89   394.1  839.95   405.2   845.3   425.2  860.53
#Mann= 5 ,-1,0
       0      .1       0  203.82    .045       0   218.1      .1       0
  332.67     .06       0  357.67      .1       0
Bank Sta=203.82,218.1
XS Rating Curve= 0 ,0
Exp/Cntr(USF)=0,0
Exp/Cntr=0.3,0.1

Type RM Length L Ch R = 1 ,6900    ,299.3,299.1,296.4
XS GIS Cut Line= 6
1651019.16961434554985.0077815061651011.76050842555072.222830176
1651004.32646817555146.8585076781650993.28712018555246.247088417
1650989.86193018555321.2813871651650986.01088801555408.920319512
#Sta/Elev= 30
       0     908    14.7  900.09    34.5  886.37    44.3  880.82    64.1  872.75
    87.1  862.02   110.2  854.23   136.6  840.05   143.2  837.47   158.1  833.86
   172.8  828.27   186.1  824.97   199.3   822.4  205.17820.0404   209.2  819.01
   212.5  818.95   215.8  819.02  219.26820.0415   225.7  823.91     229  824.47
   255.4  825.64   268.6  826.87   281.7  827.18     308  830.26     348  841.76
   370.4  845.78   376.9  847.57   393.4  853.85     403  858.04   425.4  869.86
#Mann= 5 ,-1,0
       0      .1       0  205.17    .045       0  219.26      .1       0
  292.53     .05       0  357.65      .1       0
Bank Sta=205.17,219.26
XS Rating Curve= 0 ,0
Exp/Cntr(USF)=0,0
Exp/Cntr=0.3,0.1

Type RM Length L Ch R = 1 ,6601    ,299.6,300.6,301.8
XS GIS Cut Line= 6
1650695.79165217554967.6905589251650701.53048584555055.711052179
1650703.80016634555131.1465968341650708.07935725 555231.07192193
1650712.66300951555305.9316803371650718.01011167555393.268119842
#Sta/Elev= 30
       0  874.77    28.7  865.98    41.9  863.59    48.5  861.64    74.8  850.74
    78.1  849.09    87.9  841.87    94.5  837.96   107.6   832.6     124  820.78
   127.3  819.06   163.4  815.06   173.3  815.67   183.1  814.88   196.3  816.28
   199.5  815.97   207.8813.0315   219.2  812.19  225.87 813.032   232.4  815.36
   242.2  821.99   248.8  824.99   265.2  828.84   294.8  837.32   327.7  844.15
     354   848.2     377  856.26   390.1  859.11   406.6   865.9   426.2  876.09
#Mann= 5 ,-1,0
       0      .1       0   207.8    .045       0  225.87      .1       0
  313.69     .05       0  426.19      .1       0
Bank Sta=207.8,225.87
XS Rating Curve= 0 ,0
Exp/Cntr(USF)=0,0
Exp/Cntr=0.3,0.1

Type RM Length L Ch R = 1 ,6300    ,303.7,307.1,308.8
XS GIS Cut Line= 6
1650457.31673542554958.9825710951650421.08846143555042.939096093
1650412.15868926555117.4546950911650403.27452068555217.061123177
1650397.04651476555291.8021154251650389.77946892555378.999775678
#Sta/Elev= 30
       0  846.88     8.6  844.01    22.5  835.64    33.6  834.26    40.7  832.17
    58.6  824.54    69.3  818.47      80  815.83   110.6  813.96   153.6  809.73
   183.3  808.69   193.2  806.38     203  806.75  208.82805.0566   216.2  803.97
  223.24805.0567   229.4  806.78   239.3  811.34     242  811.91   252.4  812.34
   272.2  816.75   295.2  818.56   311.7  824.72   324.9  833.46   331.5  836.38
   361.1  840.52   367.7  842.58   377.6  844.16   410.5  858.34     429  869.01
#Mann= 5 ,-1,0
       0      .1       0      80     .05       0  208.82    .045       0
  223.24     .05       0  391.49      .1       0
Bank Sta=208.82,223.24
XS Rating Curve= 0 ,0
Exp/Cntr(USF)=0,0
Exp/Cntr=0.3,0.1

Type RM Length L Ch R = 1 ,5993    ,295.3,293.1,290.8
XS GIS Cut Line= 6
1650275.69734801554789.6951799991650246.06026818554872.022771254
1650220.65677567554942.5895592571650172.91244859555034.261948094
1650118.19339792555098.6725804211650053.79162385555169.462465093
#Sta/Elev= 30
       0  867.68    20.9   858.6    26.3  857.14    62.8   851.4    90.4  844.94
   104.6   842.6   111.6  840.41   118.5   835.8   125.5  830.02   146.4  808.04
   149.9  804.83   153.4  802.74   156.9  801.74   164.7  800.93   179.2  802.29
   193.8  802.03   197.3  801.51  203.25 799.333   208.3  798.07  220.42799.3345
   230.3  800.28   245.3   803.3     290  803.46   332.4  806.28   345.9   808.9
   378.4  818.43   410.1  825.63     425  832.66   438.3  836.15   446.1  841.02
#Mann= 5 ,-1,0
       0      .1       0  203.25    .045       0  220.42      .1       0
  305.86     .05       0  440.38      .1       0
#XS Ineff= 2 , 0
          177.74  809.57
Permanent Ineff=
       F       F
Bank Sta=203.25,220.42
XS Rating Curve= 0 ,0
Exp/Cntr(USF)=0,0
Exp/Cntr=0.3,0.1

Type RM Length L Ch R = 1 ,5700    ,292.3,300.1,304.4
XS GIS Cut Line= 6
1649976.47124043554698.5080264211649951.33743243554782.514748171
1649931.16227593554854.9404563461649911.86474234554953.060995013
1649895.00453985555026.1874891671649874.92813642555111.422226846
#Sta/Elev= 30
       0  845.53      13  842.72      37  839.91    43.8  838.31    57.5  832.68
    81.5   824.7    91.7  820.19   125.8  811.31   132.6  808.24   150.5   798.7
   156.4  797.82   169.9  798.15     190  796.98   194.6  795.97   200.3793.0589
   206.7  792.14   217.7793.0577   226.8  795.82   236.8  803.12   240.1  804.25
   250.2  805.44   266.9   812.8   278.1  816.85   302.7  822.85   320.8  825.85
   364.6  839.35   378.1  842.84   398.3  855.02   411.8   864.3   425.5  870.62
#Mann= 3 ,-1,0
       0      .1       0   200.3    .045       0   217.7      .1       0
Bank Sta=200.3,217.7
XS Rating Curve= 0 ,0
Exp/Cntr(USF)=0,0
Exp/Cntr=0.3,0.1

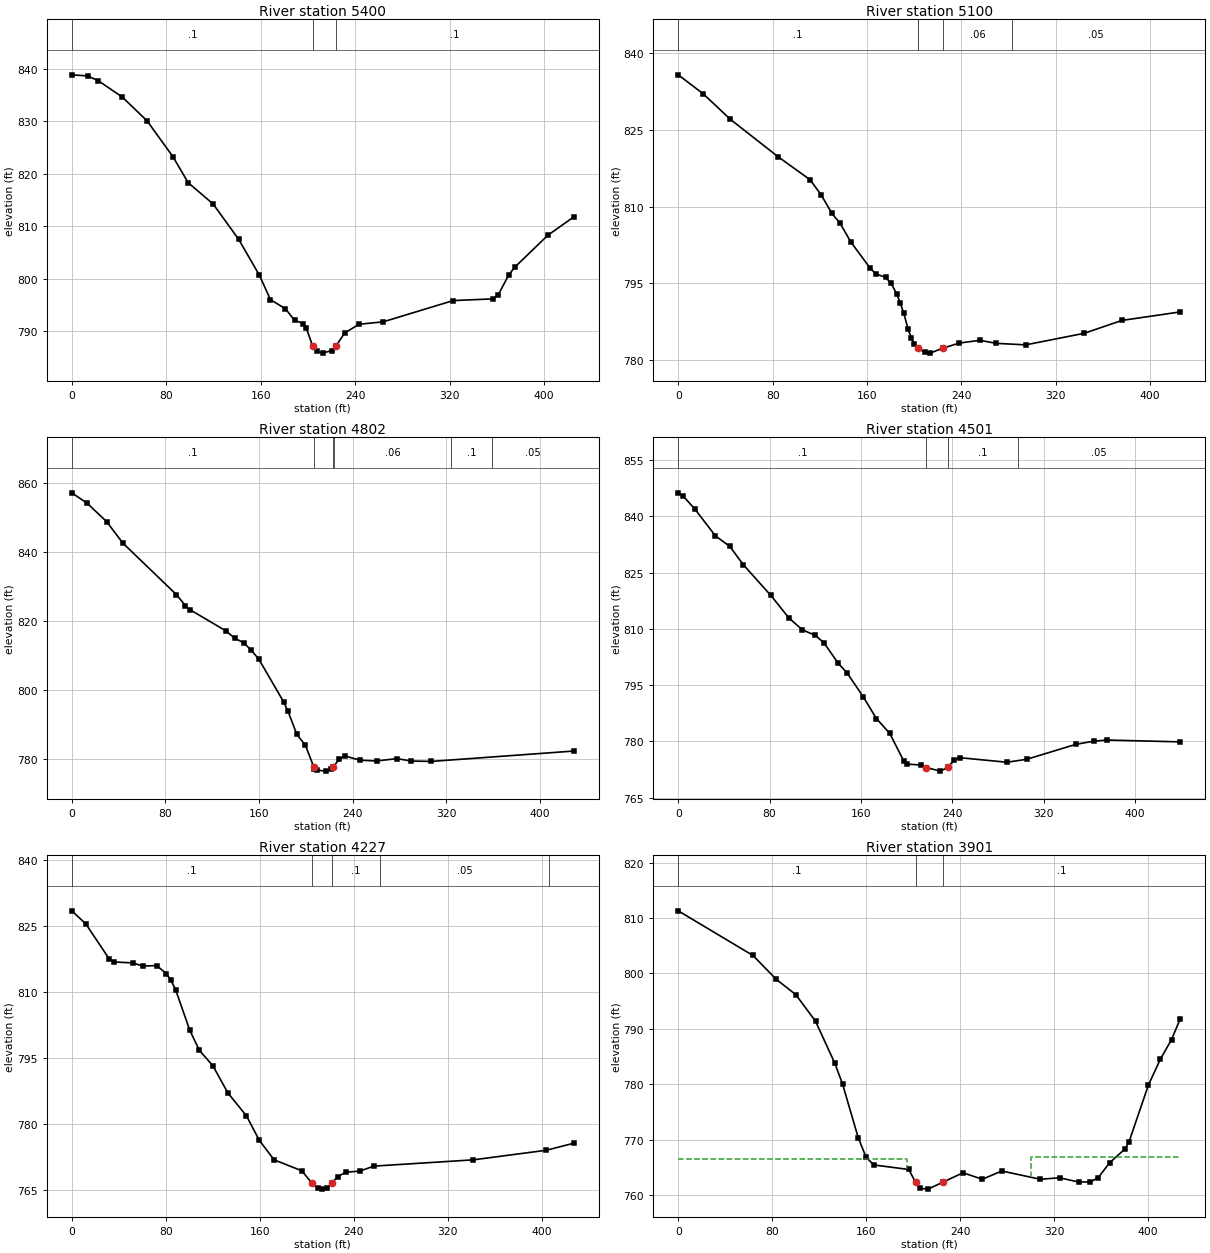
Type RM Length L Ch R = 1 ,5400    ,300.1,300,298.2
XS GIS Cut Line= 6
1649838.62768409554594.8366458421649773.26692243554653.274193004
1649717.66073443554703.706834927 1649642.4548481554769.616808087
1649586.01040718554819.0031922611649523.85534775554880.672032177
#Sta/Elev= 30
       0  838.86    13.4  838.65    22.2  837.77    42.8  834.63    63.8  830.09
    85.6   823.3    98.6  818.32   119.8  814.25   141.4  807.52   158.9  800.71
   168.3  796.05     181  794.31   188.7  792.11   196.2  791.49   198.5  790.74
  204.13787.1603   207.8  786.19   212.5  785.86   220.2  786.35  223.71787.1615
   231.1  789.69   243.4  791.36   263.8  791.82   323.1  795.87   356.6  796.19
   361.2  796.94   370.3  800.81   375.1  802.19   403.3  808.31   425.3  811.81
#Mann= 3 ,-1,0
       0      .1       0  204.13    .045       0  223.71      .1       0
Bank Sta=204.13,223.71
XS Rating Curve= 0 ,0
Exp/Cntr(USF)=0,0
Exp/Cntr=0.3,0.1

Type RM Length L Ch R = 1 ,5100    ,298.3,297.7,295
XS GIS Cut Line= 6
1649595.71019092554415.8356915121649527.58139017554471.544897676
1649476.40727992554526.3738562611649408.17513293554599.479025006
  1649356.770052554654.0924328421649295.94340201554717.010614082
#Sta/Elev= 30
       0   835.7    21.2  831.99    44.2  827.01    84.8  819.69   111.7  815.24
     121  812.32   130.3  808.65   137.2  806.72   146.2  803.11   162.8  797.94
   167.4  796.89   175.7  796.18   180.5     795   185.3  792.87   188.3   791.1
   191.1  789.22   194.9  786.03   197.6   784.4   199.7  783.28  203.25782.3672
     209  781.55   213.5  781.41  224.06782.3668   238.2  783.37   255.6  783.91
   269.5  783.32   294.4  783.02   344.1  785.28     376  787.79   425.5  789.45
#Mann= 5 ,-1,0
       0      .1       0  203.01     .06       0  203.25    .045       0
  224.06     .06       0  283.01     .05       0
Bank Sta=203.25,224.06
XS Rating Curve= 0 ,0
Exp/Cntr(USF)=0,0
Exp/Cntr=0.3,0.1

Type RM Length L Ch R = 1 ,4802    ,295.5,301.5,305
XS GIS Cut Line= 6
  1649382.766063 554151.95859459  1649337.451193554227.579834417
1649298.18093035554292.4445340931649250.62557925554380.720276177
1649217.35956967554447.9438950121649158.04866467 554514.97656934
#Sta/Elev= 30
       0   857.2    13.1  854.19    29.8  848.83    43.5  842.66    89.4  827.65
    97.1  824.46   100.9  823.29   131.6  817.14   139.3  814.97     147  813.65
   153.3  811.51   159.7  808.95     181  796.49   184.7  793.76   192.2  787.12
   199.6  783.87  206.62777.7252   207.3  777.18   209.7  776.71     217  776.43
   221.5  776.96  223.52 777.726   228.4  779.91   233.2  780.86     246   779.6
   260.6  779.38   277.7  780.06   289.9  779.36     307  779.25   428.8  782.26
#Mann= 6 ,-1,0
       0      .1       0  206.62    .045       0  223.52      .1       0
  223.99     .06       0  324.26      .1       0  359.26     .05       0
Bank Sta=206.62,223.52
XS Rating Curve= 0 ,0
Exp/Cntr(USF)=0,0
Exp/Cntr=0.3,0.1

Type RM Length L Ch R = 1 ,4501    ,275.8,273.6,268.6
XS GIS Cut Line= 6
1649225.24045943554044.4335471691649147.27079909554100.326808095
1649077.57507233554141.9576303361648992.69991401554194.857458919
1648929.64262542554235.463020757 1648856.0761715554282.835629418
#Sta/Elev= 30
       0  846.27     4.4  845.38    14.7  841.89    32.6  834.78    45.2  831.97
    56.9  827.12    81.1   818.9    96.7  812.98   108.6  809.74   120.1  808.24
   127.7  806.24     140  800.83   147.9  798.21   162.1  791.83   173.5  786.07
   185.1  782.16   197.4   774.8   200.6  773.91   212.2  773.69  217.22773.0172
   229.4  772.05  235.93773.0177   241.8  775.05     247  775.62   287.8  774.42
   305.2  775.21   348.2   779.2   363.7  780.03   375.7  780.34   439.6  779.85
#Mann= 4 ,-1,0
       0      .1       0  217.22    .045       0  235.93      .1       0
  297.13     .05       0
Bank Sta=217.22,235.93
XS Rating Curve= 0 ,0
Exp/Cntr(USF)=0,0
Exp/Cntr=0.3,0.1

Type RM Length L Ch R = 1 ,4227    ,328.8,325.8,320.1
XS GIS Cut Line= 5
1648999.36936414553802.3063943571648948.59387514553873.558876533
 1648905.0713244553934.6332294531648798.92930004554085.032863024
1648755.86068133554153.316999014
#Sta/Elev= 30
       0  828.51    11.9  825.56    32.1  817.47    36.1  816.88    52.2  816.66
    60.3  815.95    72.3  816.05    80.4  814.25    84.4  812.74    88.5  810.46
   100.5  801.31   108.6  796.78   120.1  793.27   132.8  787.12   148.7  781.87
   159.6  776.32   172.2  771.88   195.7   769.4  204.44  766.59   209.2  765.44
   213.2  765.22   217.2  765.44   221.2  766.54   226.3  768.06   233.3  769.08
   245.2  769.31   256.9  770.45   341.7  771.88   403.9  774.06   427.3  775.67
#Mann= 5 ,-1,0
       0      .1       0  204.44    .045       0   221.2      .1       0
  262.49     .05       0  406.57      .1       0
Bank Sta=204.44,221.2
XS Rating Curve= 0 ,0
Exp/Cntr(USF)=0,0
Exp/Cntr=0.3,0.1

Type RM Length L Ch R = 1 ,3901    ,337.6,337.4,327.5
XS GIS Cut Line= 6
1648596.06914559553699.8748530891648583.17579867553786.419627503
1648572.12628008 553860.601237671648559.98194742553959.895658508
1648563.61448608554035.9663725051648569.56329308554124.599397346
#Sta/Elev= 30
       0   811.3    63.6  803.24    83.5  798.93   100.1  796.17   116.9  791.37
   133.3  783.79   139.9  780.04   153.2  770.38   159.8  766.89   166.4  765.43
   196.2  764.61  202.06  762.33   206.1  761.19   212.7  761.06  225.38  762.32
   242.5  764.01     259  762.84   275.4  764.34   308.3  762.84   324.7  763.11
   341.1  762.33     351  762.38   357.6  763.14   367.4  765.84   380.6  768.36
   383.9  769.65   400.3  779.83   410.5  784.51     420  788.05   427.5  791.84
#Mann= 3 ,-1,0
       0      .1       0  202.06    .045       0  225.38      .1       0
#XS Ineff= 2 , 0
          194.95  766.45  300.36          766.79
Permanent Ineff=
       F       F
Bank Sta=202.06,225.38
XS Rating Curve= 0 ,0
Exp/Cntr(USF)=0,0
Exp/Cntr=0.3,0.1

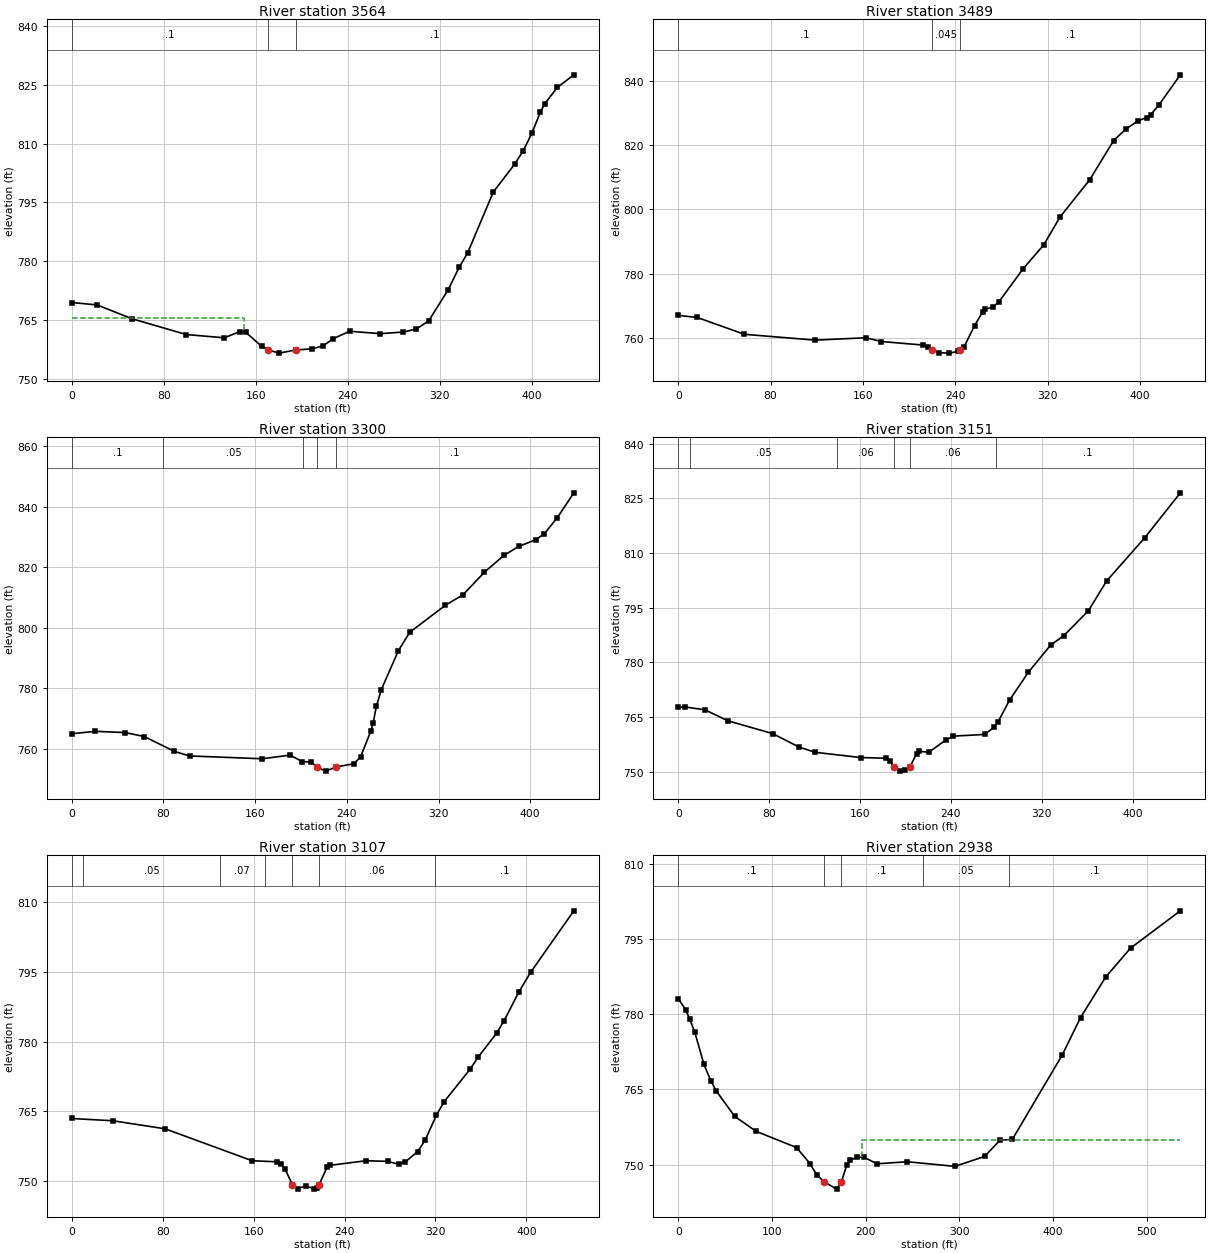
Type RM Length L Ch R = 1 ,3564    ,76.9,75.2,69
XS GIS Cut Line= 4
1648257.07362855553810.1516799921648291.13573346553955.077048457
1648379.58721542554047.915698796 1648454.8690188554188.763885267
#Sta/Elev= 30
       0  769.47    22.1  768.85    52.5  765.31    99.6   761.3   132.6  760.46
   146.2  762.04   151.3  761.88   165.2  758.29  170.82757.3569   180.4  756.55
  194.67757.3572   209.3  757.64   218.6  758.41   227.7  760.26   241.8  762.13
   268.5  761.52   288.6  761.94   299.8   762.7   310.5  764.78   327.5  772.73
     337  778.45   344.4  782.13   366.7  797.66   385.3  804.77   392.8  808.25
   400.2  812.63   407.7  818.08   411.4  820.18   422.5  824.37   436.8  827.58
#Mann= 3 ,-1,0
       0      .1       0  170.82    .045       0  194.67      .1       0
#XS Ineff= 2 , 0
          149.46  765.64
Permanent Ineff=
       F       F
Bank Sta=170.82,194.67
XS Rating Curve= 0 ,0
Exp/Cntr(USF)=0,0
Exp/Cntr=0.3,0.1

Type RM Length L Ch R = 1 ,3489    ,174.7,189,198.5
XS GIS Cut Line= 4
1648214.25128432553812.4714242541648267.23965154554008.855293931
 1648313.5977943554060.3296604091648376.81068391554209.573802845
#Sta/Elev= 30
       0  766.93    16.5  766.27    57.3  761.02   118.5   759.2   162.6  759.94
   175.9  758.76   212.2  757.66   216.7  757.08  219.78  756.18   225.5  755.28
   234.3  755.14   242.2  755.66  244.27756.1788   247.6  757.15   256.6  763.72
   263.6  768.02   265.9  768.79   272.7  769.62   277.4  771.02   298.7   781.5
   316.5  788.94   330.8  797.73   356.3  809.26   377.1  821.54   387.8  825.16
   398.5  827.75   405.6  828.68   409.2  829.62   416.3  832.65   434.8  842.05
#Mann= 3 ,-1,0
       0      .1       0  219.78    .045       0  244.27      .1       0
Bank Sta=219.78,244.27
XS Rating Curve= 0 ,0
Exp/Cntr(USF)=0,0
Exp/Cntr=0.3,0.1

Type RM Length L Ch R = 1 ,3300    ,146.9,149.1,150.3
XS GIS Cut Line= 6
1648146.23769617553755.374742091 1648151.8751521553850.419499502
1648142.15240251553926.7156067491648099.65314367554017.325661749
1648062.85105193554083.9150955081648019.55126975554162.560279429
#Sta/Elev= 30
       0  765.06    20.6  765.86    46.7  765.44    63.3  764.13    89.6  759.22
   102.8  757.73   166.2   756.8   190.4     758   201.2  755.87   208.5  755.74
  213.89754.1126   221.4  752.72   230.9754.1127   246.1  755.14     252   757.4
   260.9  765.91   262.9  768.48   265.8  774.11   270.1  779.61     285  792.47
   294.9  798.52     326  807.46   341.3  810.88   360.1  818.38     377  823.89
   389.9  826.86   404.9  829.09   412.4  831.08   423.7  836.38   438.1  844.56
#Mann= 5 ,-1,0
       0      .1       0      80     .05       0  202.12      .1       0
  213.89    .045       0   230.9      .1       0
Bank Sta=213.89,230.9
XS Rating Curve= 0 ,0
Exp/Cntr(USF)=0,0
Exp/Cntr=0.3,0.1

Type RM Length L Ch R = 1 ,3151    ,43.7,44,44.6
XS GIS Cut Line= 3
1648109.93681245553767.6683178921647936.47030178553974.083774725
1647913.21222214554144.643025442
#Sta/Elev= 30
       0  767.63     5.8  767.76    23.6  766.97    43.4  763.99      83  760.46
   106.3  756.76   120.3  755.33   160.8  753.88   183.1  753.69   186.5  752.91
  189.68751.2935   194.8  750.16   199.6  750.43  203.76751.2944   209.8  754.91
   212.2  755.61   220.4  755.32   235.3  758.65   242.2  759.76   269.6  760.22
   278.2  762.25   281.5  763.71   291.5  769.62     308  777.24   327.9   784.8
   339.2  787.28     361  794.17     377  802.32   410.7  814.22   441.8  826.48
#Mann= 6 ,-1,0
       0      .1       0      10     .05       0     140     .06       0
  189.68    .045       0  203.76     .06       0  279.63      .1       0
Bank Sta=189.68,203.76
XS Rating Curve= 0 ,0
Exp/Cntr(USF)=0,0
Exp/Cntr=0.3,0.1

Type RM Length L Ch R = 1 ,3107    ,169.5,168.1,163.1
XS GIS Cut Line= 3
1648080.37966957553735.203915057 1647906.9131589 553941.61937189
1647883.65507926554112.178622607
#Sta/Elev= 30
       0  763.46    36.2  762.97    82.2  761.24   158.7  754.38   180.5  754.15
   184.2  753.65   187.5  752.66  194.15749.2663   198.9  748.39   206.2  749.01
   213.1  748.28   215.5  748.48  217.67749.2687   224.6  752.95   227.1  753.39
   258.9  754.38   277.9  754.25   287.8  753.61   293.6  754.16   304.4  756.35
     311  758.82   320.9  764.19   327.6  767.05   350.7  774.11   357.4  776.59
   373.9  781.82   380.5  784.49   393.2  790.56   403.7  794.85   441.8  808.09
#Mann= 7 ,-1,0
       0      .1       0      10     .05       0     130     .07       0
     170     .06       0  194.15    .045       0  217.67     .06       0
  319.63      .1       0
Bank Sta=194.15,217.67
XS Rating Curve= 0 ,0
Exp/Cntr(USF)=0,0
Exp/Cntr=0.3,0.1

Type RM Length L Ch R = 1 ,2938    ,310.7,297.1,286.4
XS GIS Cut Line= 4
1647819.03391452553679.5851382471647816.18391663553800.916364872
 1647751.8174205553949.0310901711647791.13971339554199.059070062
#Sta/Elev= 30
       0  783.11     7.8  780.92    12.3  779.02    17.6  776.45    27.4  770.03
    34.7  766.76    40.6   764.7    60.3  759.62    83.2  756.64   126.3  753.41
   140.6  750.22   147.8  747.99   155.9  746.56   169.2  745.12  174.17746.5579
     180  749.96   183.5  750.89   191.1  751.44   197.8  751.52   212.2  750.17
   244.4  750.58   295.5  749.66   327.1  751.64   343.4  754.85   356.7  755.05
   409.9  771.85   429.5  779.33   456.3   787.4   482.9  793.18     536  800.61
#Mann= 5 ,-1,0
       0      .1       0   155.9    .045       0  174.17      .1       0
  261.36     .05       0  352.86      .1       0
#XS Ineff= 2 , 0
                          196.25          754.96
Permanent Ineff=
       F       F
Bank Sta=155.9,174.17
XS Rating Curve= 0 ,0
Exp/Cntr(USF)=0,0
Exp/Cntr=0.3,0.1

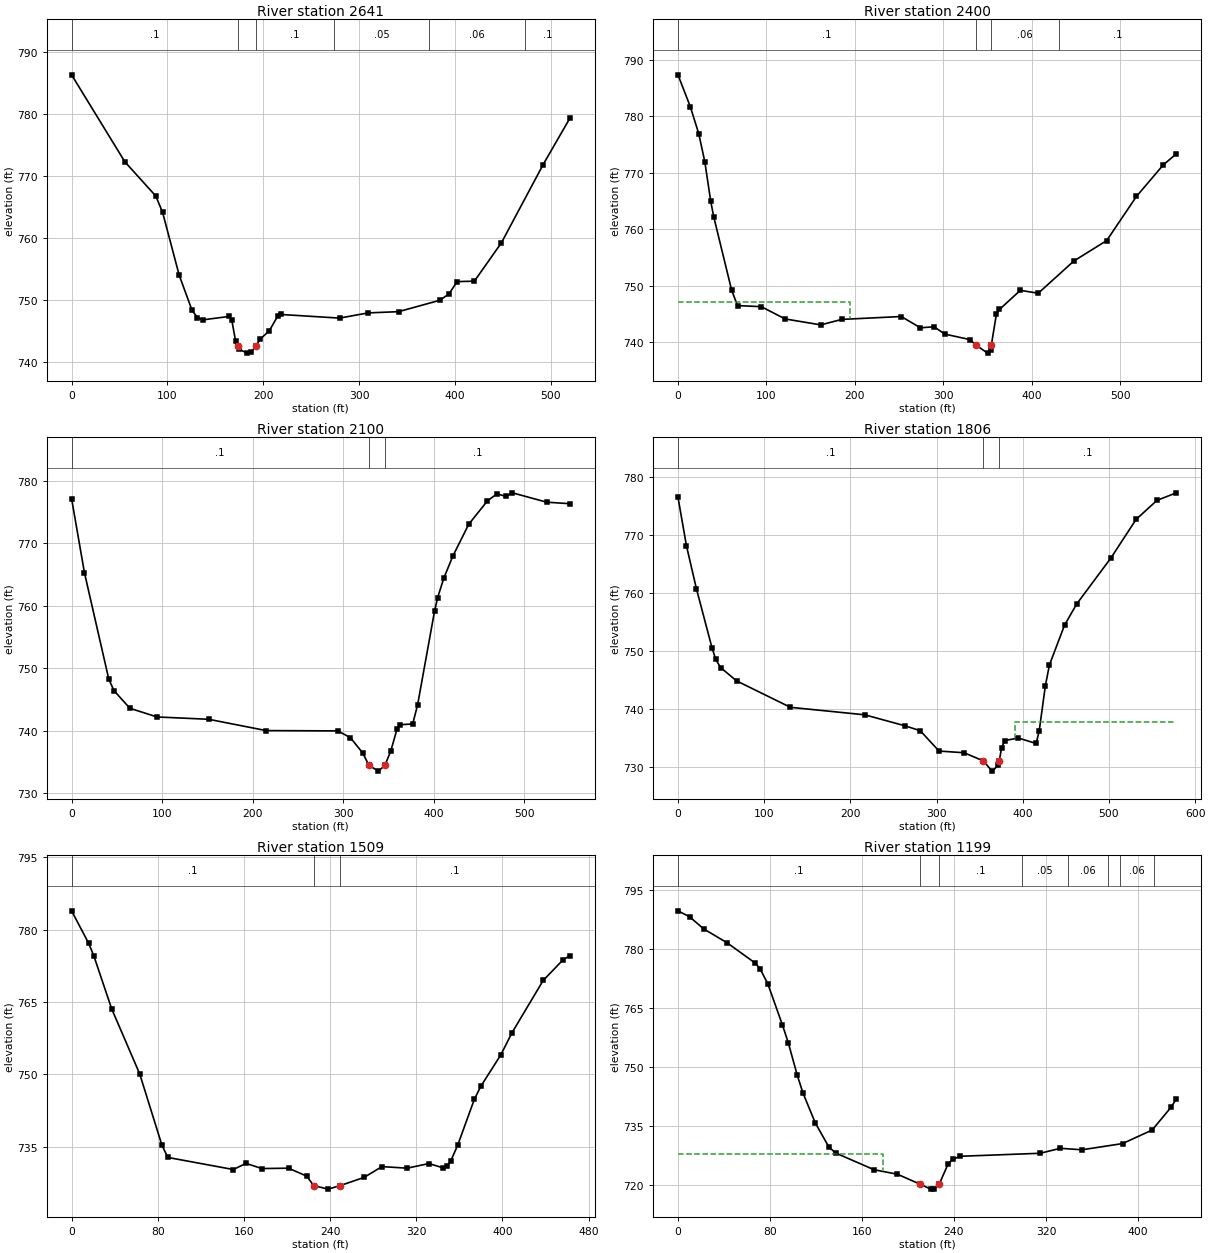
Type RM Length L Ch R = 1 ,2641    ,229.1,241,241.7
XS GIS Cut Line= 4
1647457.92416328553728.2374243711647502.24769758553829.390762789
1647635.04846097553923.9066214211647735.60775041554149.097118109
#Sta/Elev= 30
       0  786.36    55.6  772.33    87.9   766.8      95  764.16   112.3  754.04
   125.7  748.37   131.4  747.18     137  746.83   164.1  747.37   167.2  746.78
   171.2  743.39  173.52742.5935   175.2  742.05   183.3  741.46   187.6  741.59
  192.17742.5925     197  743.74   206.4  745.07   215.5  747.53   218.2   747.7
   279.7  747.11   309.5  747.95   341.3  748.15   384.4  749.99   393.9  751.02
   402.4     753   420.4  753.07   448.6  759.26   492.2  771.89   520.1  779.37
#Mann= 6 ,-1,0
       0      .1       0  173.52    .045       0  192.17      .1       0
  273.44     .05       0  373.44     .06       0  473.44      .1       0
Bank Sta=173.52,192.17
XS Rating Curve= 0 ,0
Exp/Cntr(USF)=0,0
Exp/Cntr=0.3,0.1

Type RM Length L Ch R = 1 ,2400    ,292.6,300.3,303
XS GIS Cut Line= 4
1647397.20639281553743.1241227161647486.27838618554133.947475761
1647503.31969067554206.9857155081647523.20121258554292.197159261
#Sta/Elev= 30
       0   787.3      14  781.64    23.5  776.89    30.3  771.97      37  764.99
    40.4  762.22    60.6  749.28    67.3  746.52    94.2  746.33   121.1  744.16
   161.5  743.11   185.1  744.08   252.4  744.59   274.1  742.59   289.4  742.78
   301.7  741.48   329.8  740.52  337.01739.5295   349.9  738.12   353.3  738.63
  354.22739.5311     360  745.06   363.4  745.83     387  749.22   407.2   748.7
   447.6  754.41   484.6  758.01   518.3  765.82   548.6  771.39   563.3  773.33
#Mann= 4 ,-1,0
       0      .1       0  337.01    .045       0  354.22     .06       0
  430.84      .1       0
#XS Ineff= 2 , 0
          194.51  747.09
Permanent Ineff=
       F       F
Bank Sta=337.01,354.22
XS Rating Curve= 0 ,0
Exp/Cntr(USF)=0,0
Exp/Cntr=0.3,0.1

Type RM Length L Ch R = 1 ,2100    ,282.8,293.5,298.1
XS GIS Cut Line= 6
1647274.30884966553742.2777266991647233.65093867553951.071201086
1647210.99776876554022.5713861731647180.73929909554117.883531511
 1647158.0877696554189.3781391681647131.65967284554272.789717749
#Sta/Elev= 30
       0  777.13    14.2  765.27      41  748.28    46.7  746.41    64.4  743.57
    94.4  742.18   151.3  741.81   214.8     740     294  739.95   307.8  738.87
   321.5  736.41  328.21734.4532   338.7  733.51  346.02734.4528   352.5  736.77
   359.4  740.28   362.8  740.94   376.6  741.06     382  744.09   400.7  759.09
   404.1  761.26     411  764.41   420.9  767.92   438.5  773.03   459.2  776.78
   469.5  777.88   479.8   777.5   486.7  778.06   524.6  776.56   550.2  776.32
#Mann= 3 ,-1,0
       0      .1       0  328.21    .045       0  346.02      .1       0
Bank Sta=328.21,346.02
XS Rating Curve= 0 ,0
Exp/Cntr(USF)=0,0
Exp/Cntr=0.3,0.1

Type RM Length L Ch R = 1 ,1806    ,305.5,297.1,284.5
XS GIS Cut Line= 3
 1647240.5343572553729.7224370871647151.75085506553832.284249099
1646751.76607567554021.732477084
#Sta/Elev= 30
       0  776.46     9.8  768.11    21.4  760.68    39.4  750.54    43.7  748.53
    49.4  747.09      68  744.79   130.5  740.23   216.7  738.94     263  737.06
   281.1   736.2   302.9  732.69     332   732.4  354.26730.9982   364.5  729.23
   371.9  730.28  372.77730.9977   375.5  733.25   379.2   734.5   394.9  734.94
   415.5     734   419.1  736.13   426.3  743.97     431  747.54   448.5  754.38
   462.6  758.04   502.4  765.99   531.6  772.64   555.8  775.91   578.2  777.21
#Mann= 3 ,-1,0
       0      .1       0  354.26    .045       0  372.77      .1       0
#XS Ineff= 2 , 0
                          390.76          737.77
Permanent Ineff=
       F       F
Bank Sta=354.26,372.77
XS Rating Curve= 0 ,0
Exp/Cntr(USF)=0,0
Exp/Cntr=0.3,0.1

Type RM Length L Ch R = 1 ,1509    ,303.9,310.4,316.9
XS GIS Cut Line= 6
1646899.88454585553574.5151956681646846.54016434553656.111489177
1646800.19872159553728.3203342561646782.96942534553827.417576998
1646766.23323834553906.2582985911646724.64539501553995.243684918
#Sta/Elev= 30
       0  783.88    15.9  777.13    20.6  774.59    37.2  763.59    63.3  750.06
    83.8  735.38    89.3  732.79   150.2  730.28   161.9  731.56   176.7  730.48
   201.5  730.56   218.3  728.91  224.84726.9494   238.3  726.22  249.34726.9498
   271.6  728.65   288.2  730.89   311.5  730.56   331.8  731.52   345.3   730.6
   348.6  730.95     352  732.03   358.5  735.31   373.9  744.79   379.9   747.5
   398.6  754.06   408.9  758.61   437.9  769.46     456  773.65   462.7  774.61
#Mann= 3 ,-1,0
       0      .1       0  224.84    .045       0  249.34      .1       0
Bank Sta=224.84,249.34
XS Rating Curve= 0 ,0
Exp/Cntr(USF)=0,0
Exp/Cntr=0.3,0.1

Type RM Length L Ch R = 1 ,1199    ,302.5,298.8,295
XS GIS Cut Line= 6
1646750.74114335 553446.347473011646696.38856176553519.050083503
1646653.89028718553583.4475925121646595.42747758553666.015996918
1646545.89804909553722.5270387531646474.08749717553775.265778422
#Sta/Elev= 30
       0  789.75    10.1  788.24    22.3  785.17    42.8  781.61    67.4  776.42
    71.5  774.95    78.1  771.21    90.8  760.77    95.9  756.24   103.7  747.98
   108.7  743.45   119.4  735.84   131.2  729.73   137.1   728.2   170.6  723.94
   190.7  722.82  210.23 720.314   219.7  719.02   222.9  719.14  227.19720.3121
   234.9  725.42   238.9  726.63   245.6  727.37   314.9  728.13   332.4  729.39
   351.3  729.02   386.6   730.6   412.3  734.04   428.9  739.89   433.3  741.97
#Mann= 8 ,-1,0
       0      .1       0  210.23    .045       0  227.19      .1       0
   299.1     .05       0   339.1     .06       0  374.24     .05       0
  384.24     .06       0  414.24      .1       0
#XS Ineff= 2 , 0
          177.98  727.88
Permanent Ineff=
       F       F
Bank Sta=210.23,227.19
XS Rating Curve= 0 ,0
Exp/Cntr(USF)=0,0
Exp/Cntr=0.3,0.1