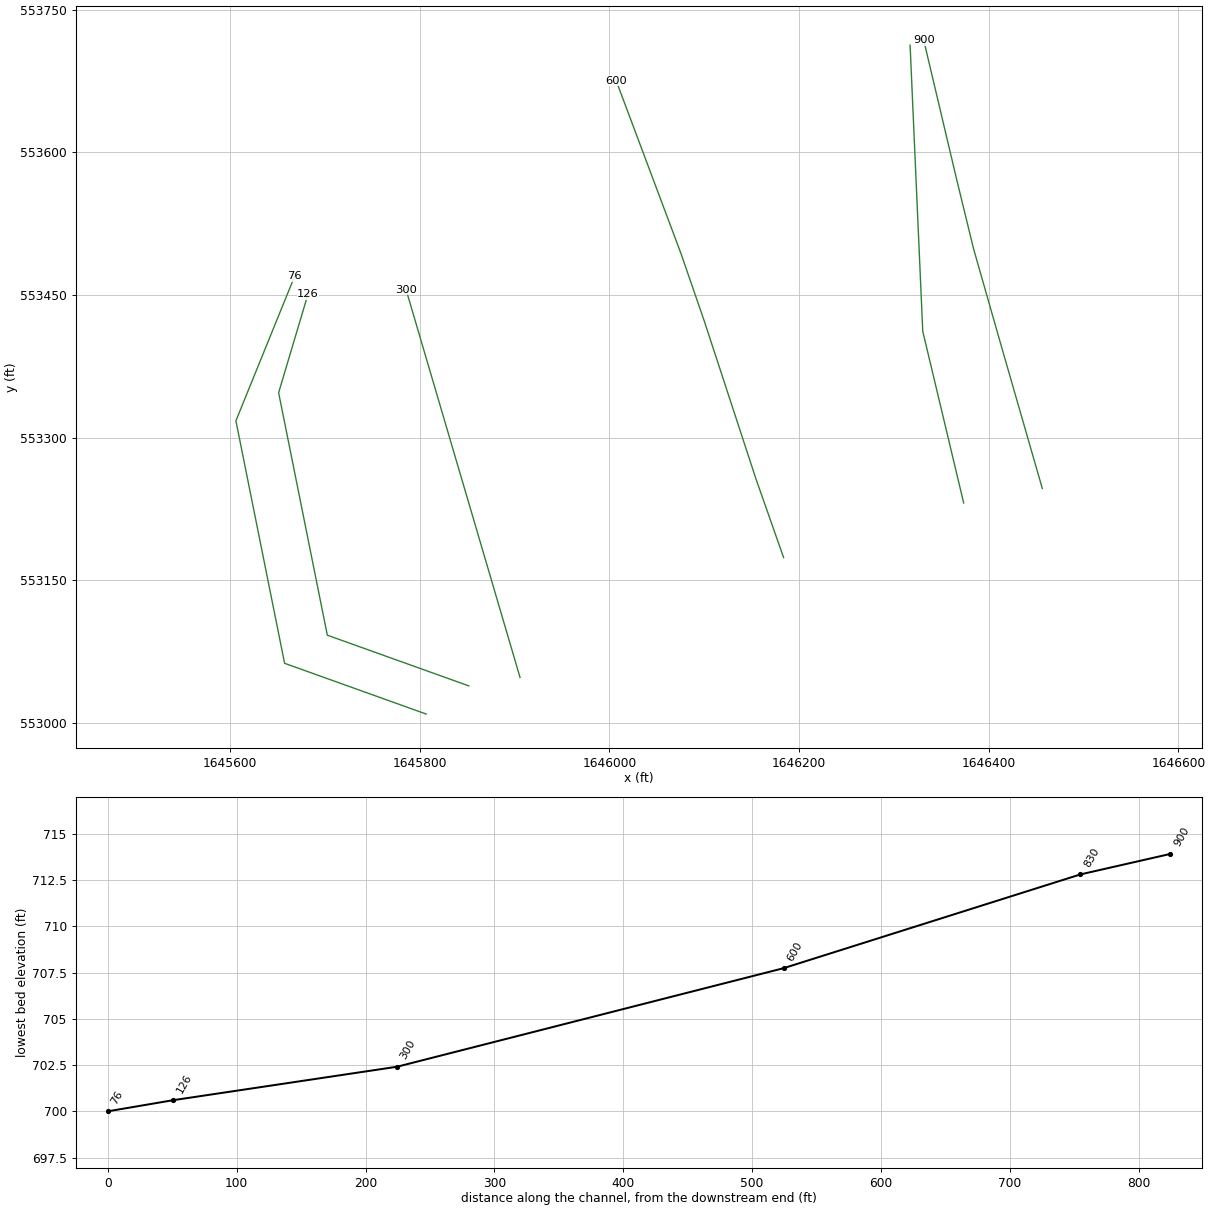
HEC-RAS study BrittRn.prj: BrittRn

--- BrittRn.g01 (geometry) --- (continued)

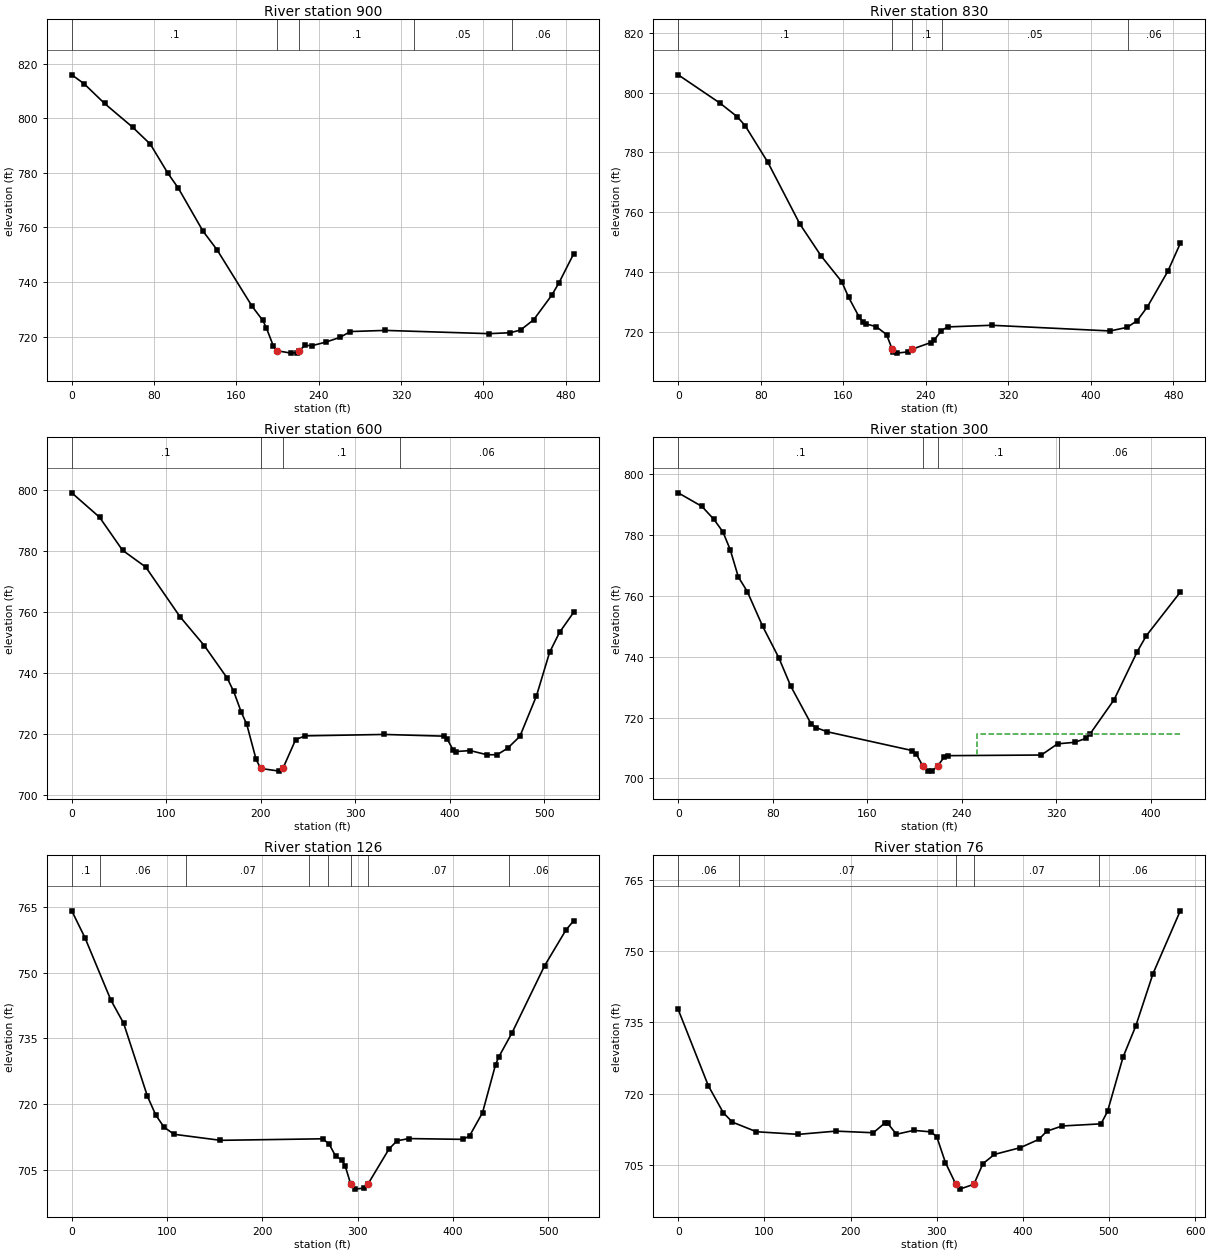
Type RM Length L Ch R = 1 ,900     ,72.2,69.9,67.2
XS GIS Cut Line= 6
1646456.52093126553246.5831087531646432.23620293 553330.64560467
1646411.42062776553402.6989382511646383.91740192553498.842774838
1646366.09821184553571.7619203331646331.39963914553718.003841567
#Sta/Elev= 30
       0  815.94      12  812.66    31.9  805.43    59.2  796.72    76.3  790.54
    93.4  779.86   103.6  774.36   127.5  758.65   141.2  751.79   175.3  731.05
   185.6  725.93     189  723.29   195.8  716.62  199.67714.7913   212.9  713.92
   218.7  714.14  221.26714.7914   226.5  716.77   233.3  716.64     247  717.97
   260.6  719.69   270.8  721.83   304.6  722.25   405.2  721.06     426  721.39
   436.1  722.38   448.9  726.16   466.5  735.17   473.4  739.65   487.9  750.44
#Mann= 5 ,-1,0
       0      .1       0  199.67    .045       0  221.26      .1       0
   332.5     .05       0  427.56     .06       0
Bank Sta=199.67,221.26
XS Rating Curve= 0 ,0
Exp/Cntr(USF)=0,0
Exp/Cntr=0.3,0.1

Type RM Length L Ch R = 1 ,830     ,228.2,230.3,233.1
XS GIS Cut Line= 3
1646373.57406314553231.3638462131646330.40125281553411.904689446
1646317.05692961553712.544441438
#Sta/Elev= 30
       0  805.93    40.5  796.46    57.3  791.88      65  788.84    86.8  776.71
     118  755.95   138.5  745.33   158.5  736.71   165.2  731.46   175.4  724.87
   178.7  723.37   182.1  722.59     192  721.65   201.9  719.03  207.34  714.16
   208.5  713.35   211.8  712.81   222.4  713.22  226.88  714.15   244.6  716.32
   247.9  717.11   255.1  720.33     261  721.58   303.7  722.13   418.6  720.23
   435.1  721.43   444.9  723.69   454.8  728.33   474.5  740.17   486.6  749.53
#Mann= 5 ,-1,0
       0      .1       0  207.34    .045       0  226.88      .1       0
  255.63     .05       0  435.63     .06       0
Bank Sta=207.34,226.88
XS Rating Curve= 0 ,0
Exp/Cntr(USF)=0,0
Exp/Cntr=0.3,0.1

Type RM Length L Ch R = 1 ,600     ,298.9,300,300.1
XS GIS Cut Line= 6
1646183.61170018553174.0773482621646154.50775576553256.616881341
1646131.09638526553327.8693635021646099.88122459553422.872454345
1646075.32615559553493.7492810931646007.07059517553675.175439064
#Sta/Elev= 30
       0  799.08    29.4  791.07    53.7  780.24    78.3  774.72   114.5  758.44
   140.3  748.92   164.5  738.28   171.4  733.89   179.5  727.01   185.2  723.12
   195.1  711.59  199.95708.6161   219.7  707.74  223.47708.6174     237   718.1
   247.1  719.32   330.6  719.78   393.6  719.22   397.1  718.44   403.7  714.65
   406.3  714.16   421.7  714.48   439.4  713.12   450.1  713.11   461.3  715.25
   474.3  719.15   491.8  732.38   505.8  746.76   516.3   753.3   531.4  759.93
#Mann= 4 ,-1,0
       0      .1       0  199.95    .045       0  223.47      .1       0
  347.53     .06       0
Bank Sta=199.95,223.47
XS Rating Curve= 0 ,0
Exp/Cntr(USF)=0,0
Exp/Cntr=0.3,0.1

Type RM Length L Ch R = 1 ,300     ,173.8,173.9,173.2
XS GIS Cut Line= 6
1645905.63883093553047.9995164281645880.89117701553131.927170083
1645859.67829293553203.8646902591645831.39521301553299.781493172
1645810.18167275553371.7190133331645785.43205035553455.645682752
#Sta/Elev= 30
       0  793.81    20.1  789.34    30.3  785.06    37.8  781.01      44  775.18
    50.9  766.17    58.5  761.38    71.4  750.04    85.1  739.69    95.3   730.3
   112.4  717.99   116.6  716.71   126.1  715.34     198  709.17   201.4  708.12
   207.2703.9844   211.6  702.41   215.1  702.54  219.51703.9871   225.3  707.13
   228.7  707.49   307.4   707.7   321.1  711.37   335.8  711.88     345  713.15
   348.5  714.54     369  725.88   388.6  741.67   396.3   746.9     425  761.18
#Mann= 4 ,-1,0
       0      .1       0   207.2    .045       0  219.51      .1       0
   322.5     .06       0
#XS Ineff= 2 , 0
                          252.71          714.53
Permanent Ineff=
       F       F
Bank Sta=207.2,219.51
XS Rating Curve= 0 ,0
Exp/Cntr(USF)=0,0
Exp/Cntr=0.3,0.1

Type RM Length L Ch R = 1 ,126     ,50.9,50.5,51.5
XS GIS Cut Line= 4
1645851.61604257553039.1283548031645702.37669819553092.428120652
1645651.01510565553347.297910075 1645682.0258785553450.990181817
#Sta/Elev= 30
       0  764.13    13.8  758.01    41.1  743.72    54.4  738.46    79.4  721.78
    88.2  717.48    96.8  714.74   107.3  713.12     156  711.74   263.3  712.09
     270  710.88   276.7  708.17   283.4  707.24   286.8  705.92  292.56701.7998
   296.8   700.6   306.8  700.84  310.87701.8029   332.9  709.79   341.3  711.64
   353.7  712.14   410.6  711.96   417.3  712.75   430.9  718.04   444.6  729.03
   448.1  730.83   461.8  736.25     496  751.58   518.6  759.81   526.7  761.89
#Mann= 8 ,-1,0
       0      .1       0      30     .06       0     120     .07       0
  248.47     .06       0  268.47     .07       0  292.56    .045       0
  310.87     .07       0  458.47     .06       0
Bank Sta=292.56,310.87
XS Rating Curve= 0 ,0
Exp/Cntr(USF)=0,0
Exp/Cntr=0.3,0.1

Type RM Length L Ch R = 1 ,76      ,,,
XS GIS Cut Line= 4
1645806.55351326553009.5712119231645657.31416888553062.870977772
1645605.95257634553317.7407671951645667.97412205553469.887371527
#Sta/Elev= 30
       0  737.72      35  721.69    52.4  716.03    62.9  714.07    90.8  712.05
   139.5   711.5     183  712.18   226.5  711.84   239.9  713.89   243.3  713.79
   253.3  711.52   273.4  712.34   293.5  712.02   300.2  710.98   310.2  705.57
  322.27701.0278   326.9     700  343.24701.0253   353.7  705.34   367.1  707.29
   397.2  708.71   418.5  710.44   427.9  712.16   445.6  713.26   490.8  713.71
   498.4  716.33   516.4  727.73   531.1  734.23   551.2  745.27   582.8  758.44
#Mann= 5 ,-1,0
       0     .06       0      70     .07       0  322.27    .045       0
  343.24     .07       0  488.47     .06       0
Bank Sta=322.27,343.24
XS Rating Curve= 0 ,0
Exp/Cntr(USF)=0,0
Exp/Cntr=0.3,0.1
LCMann Table=0

Chan Stop Cuts=-1
Use User Specified Reach Order=0
Composite Channel Slope=5